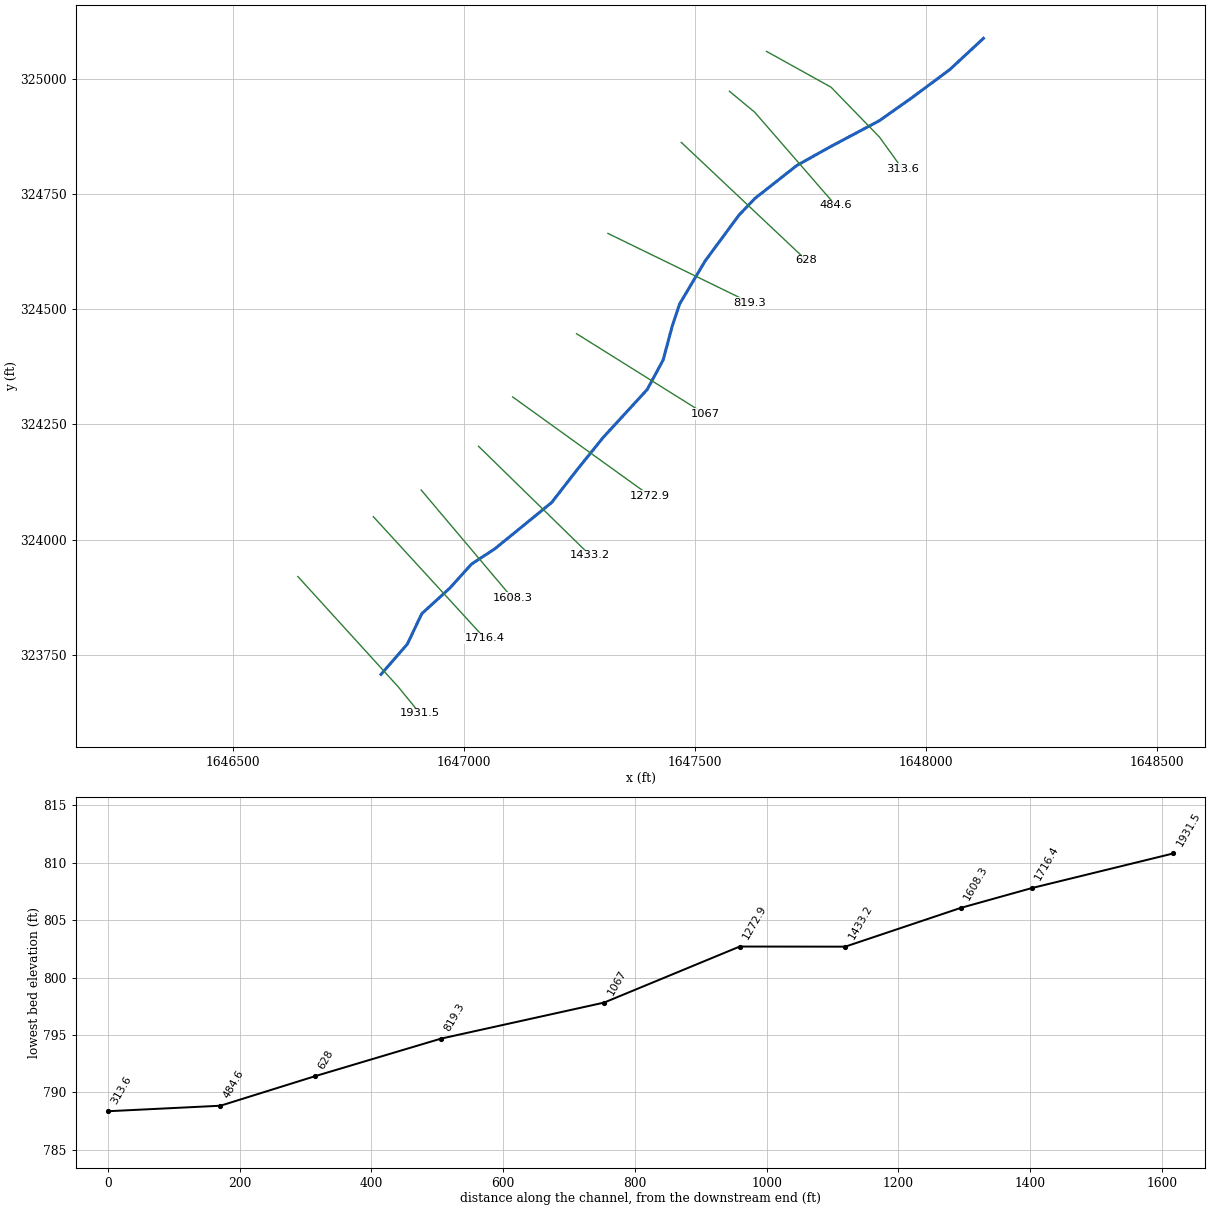
--- LIBATTLRN1.prj (project) ---

Proj Title=LIBATTLRN1
Current Plan=p01
Default Exp/Contr=0,0
English Units
Geom File=g01
Flow File=f01
Plan File=p01
BEGIN DESCRIPTION:
END DESCRIPTION:
DSS Export Rating Curves= 0
DSS Export Rating Curve Sorted= 0
DSS Export Volume Flow Curves= 0
DXF OffsetX= 0
DXF OffsetY= 0
DXF ScaleX= 0
DXF ScaleY= 0

--- LIBATTLRN1.p01 (plan) ---

Plan Title=Floodplain
Program Version=4.00
Geom File=g01
Flow File=f01
K Sum by GR=0
Std Step Tol=0.01
Critical Tol=0.01
Num of Std Step Trials=20
Max Error Tol=0.3
Flow Tol Ratio=0.001
Split Flow NTrial=30
Split Flow Tol=0.02
Split Flow Ratio=0.02
Log Output Level=0
Friction Slope Method=1
Unsteady Friction Slope Method=2
Unsteady Bridges Friction Slope Method=1
Global Log Level=0
CheckData=False
Run HTab=0
Run UNet=0
Run PostProcess=0
UNET Theta=0
UNET Theta Warmup=0
UNET ZTol=0
UNET ZSATol=0
UNET MxIter=0
UNET MaxInSteps=0
UNET DtIC=0
UNET DtMin=0
UNET MaxCRTS=0
UNET WFStab=0
UNET SFStab=0
UNET WFX=0
UNET SFX=0
UNET DSS MLevel=0
UNET DZMax Abort=0
UNET Convert EG Bridges=0
UNET Use Existing IB Tables=0
UNET Froude Limit=0
UNET Froude Power=0
Write IC File=0
Echo Input=False
Echo Output=False
Write Detailed=0

--- LIBATTLRN1.f01 (steady flow) ---

Flow Title=NFF Regression Equation
Program Version=4.10
Number of Profiles= 1
Profile Names=P100yr
River Rch & RM=LIBATTLRN1,Main            ,1931.5
693.2871
River Rch & RM=LIBATTLRN1,Main            ,484.6
721.5261
Boundary for River Rch & Prof#=LIBATTLRN1,Main            , 1
Up Type= 0
Dn Type= 3
Dn Slope=0.00269
DSS Import GetInterval= 0
DSS Import GetPeak= 0
DSS Import FillOption= 0

--- LIBATTLRN1.g01 (geometry) ---

Geom Title=USGS 10m DEM
Program Version=4.10

River Reach=LIBATTLRN1      ,Main
Reach XY= 23
     1646820.944      323707.927      1646877.92      323773.503
      1646909.17      323839.475     1646969.934      323895.031
     1647016.809      323947.114     1647067.157        323980.1
     1647133.129       324033.92      1647190.42      324080.795
      1647244.24      324150.239     1647301.531       324221.42
     1647397.018      324325.587      1647431.74      324389.823
     1647451.705      324464.475      1647467.33       324511.35
     1647522.886        324605.1     1647595.802      324704.059
     1647630.524      324740.517     1647720.802      324811.697
     1647791.983      324851.628     1647899.622       324908.92
     1647970.802      324959.267       1648052.4      325020.031
     1648125.224       325087.76

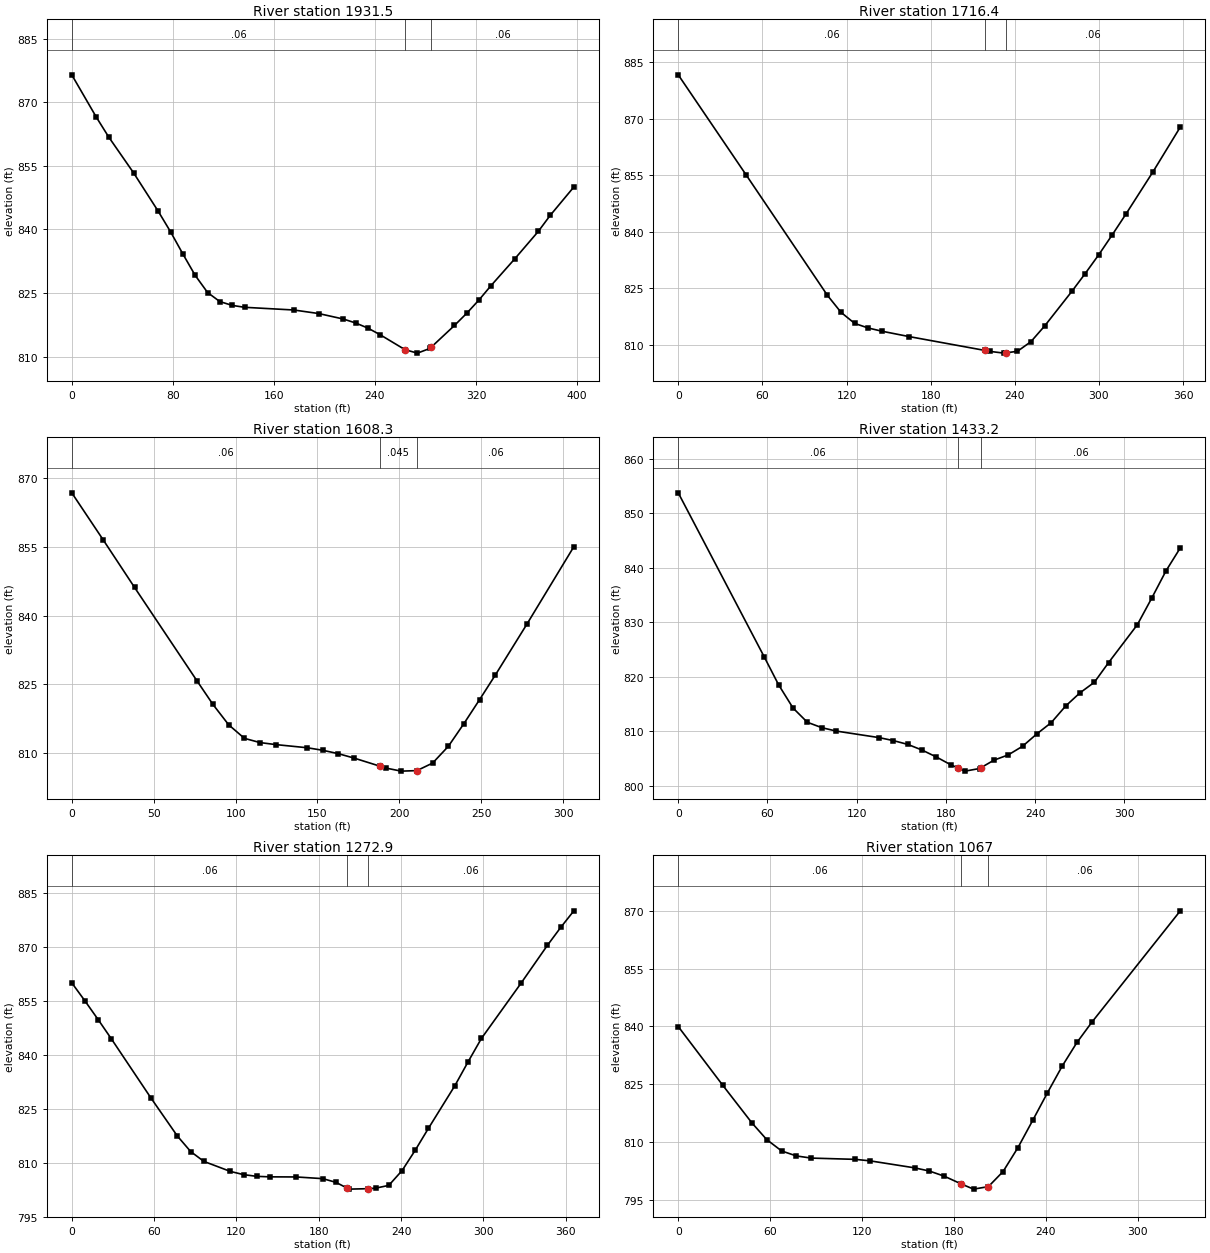
Type RM Length L Ch R = 1 ,1931.5  ,215.1,215.1,215.1
XS GIS Cut Line= 3
     1646640.967      323920.137     1646857.737      323681.425
       1646905.1      323623.273
#Sta/Elev= 30
       0  876.46    19.5  866.44    29.3  861.76    48.9  853.35    68.4  844.29
    78.2  839.43    87.9  834.22    97.7  829.14   107.5  825.11   117.2  822.97
     127  822.07   136.8  821.62   175.9  820.98   195.4  820.15     215  818.85
   224.7  817.92   234.5   816.7   244.3  815.11   263.8  811.62   273.6  810.81
   283.4  811.91   284.5  812.21   302.9  817.33   312.7  820.24   322.4  823.38
   331.8  826.72   350.6  833.04   369.3  839.54   378.7  843.31   397.4     850
#Mann= 3 , 0 , 0
       0     .06       0   263.8    .045       0   284.5     .06       0
Bank Sta=263.8,284.5
XS Rating Curve= 0 ,0
Exp/Cntr=0.3,0.1

Type RM Length L Ch R = 1 ,1716.4  ,109.1,108.1,107.2
XS GIS Cut Line= 2
     1646804.381      324049.964      1647045.93      323785.777
#Sta/Elev= 22
       0  881.69    48.4  855.12   106.4  823.12   116.1  818.61   125.8  815.68
   135.4  814.47   145.1  813.62   164.5  812.19   218.6  808.51   222.5  808.24
   232.2  807.79   233.6  807.86   241.9  808.28   251.5  810.84   261.2  814.97
   280.6  824.16   290.2  828.93   299.9  833.94   309.6  839.28   319.3  844.76
   338.6  855.99     358  867.83
#Mann= 3 , 0 , 0
       0     .06       0   218.6    .045       0   233.6     .06       0
Bank Sta=218.6,233.6
XS Rating Curve= 0 ,0
Exp/Cntr=0.3,0.1

Type RM Length L Ch R = 1 ,1608.3  ,173,175.1,177.3
XS GIS Cut Line= 2
     1646907.894      324107.854     1647105.376      323873.479
#Sta/Elev= 24
       0  866.77    19.2   856.5    38.3  846.15    76.6  825.67    86.2   820.6
    95.8  816.16   105.4  813.21   114.9  812.29   124.5  811.85   143.7  811.16
   153.2  810.61   162.8  809.86   172.4   808.9   188.1  807.14   191.6  806.74
   201.1  806.06   210.7  806.17   220.3  807.82   229.9  811.48   239.4  816.43
     249  821.68   258.6  827.04   277.8   838.1   306.5  855.02
#Mann= 3 , 0 , 0
       0     .06       0   188.1    .045       0   210.7     .06       0
Bank Sta=188.1,210.7
XS Rating Curve= 0 ,0
Exp/Cntr=0.3,0.1

Type RM Length L Ch R = 1 ,1433.2  ,156.8,160.2,163.6
XS GIS Cut Line= 2
     1647032.083      324202.736     1647273.348      323966.518
#Sta/Elev= 30
       0  853.77    57.9  823.62    67.5  818.53    77.2  814.27    86.8  811.66
    96.5  810.67   106.1  810.05   135.1  808.84   144.7  808.29   154.4  807.59
     164  806.55   173.6  805.28   183.3  803.85   188.3  803.25   192.9  802.69
   202.6  803.17   203.3  803.28   212.2  804.69   221.9  805.67   231.5  807.25
   241.2  809.54   250.8  811.59   260.5  814.64   270.1  817.05   279.8     819
   289.4  822.62   308.7  829.56   318.4  834.45     328  839.46   337.6  843.67
#Mann= 3 , 0 , 0
       0     .06       0   188.3    .045       0   203.3     .06       0
Bank Sta=188.3,203.3
XS Rating Curve= 0 ,0
Exp/Cntr=0.3,0.1

Type RM Length L Ch R = 1 ,1272.9  ,204.4,205.9,207.4
XS GIS Cut Line= 2
     1647105.941      324309.814     1647402.752      324095.708
#Sta/Elev= 30
       0     860     9.6  854.99    19.3  849.75    28.9  844.42    57.8  827.97
      77  817.44    86.7  813.13    96.3   810.4   115.6  807.62   125.2  806.73
   134.8  806.25   144.5  806.11   163.7  806.08     183  805.61   192.6  804.58
   200.6  803.01   202.2   802.7   215.6  802.82   221.5  802.97   231.1  803.74
   240.8  807.86   250.4  813.52     260  819.59   279.3  831.45   288.9  838.06
   298.6  844.54   327.4  859.84   346.7   870.4   356.4  875.38     366     880
#Mann= 3 , 0 , 0
       0     .06       0   200.6    .045       0   215.6     .06       0
Bank Sta=200.6,215.6
XS Rating Curve= 0 ,0
Exp/Cntr=0.3,0.1

Type RM Length L Ch R = 1 ,1067    ,245.3,247.7,250.1
XS GIS Cut Line= 2
     1647244.368      324446.975      1647522.13      324272.871
#Sta/Elev= 23
       0  839.99    28.9  824.84    48.2  814.95    57.8  810.66    67.5  807.72
    77.1  806.43    86.8  805.87   115.7  805.54   125.3  805.15   154.3  803.34
   163.9  802.52   173.6  801.19   184.9  799.14   192.8  797.82   202.5  798.47
   212.1  802.39   221.8  808.59   231.4  815.63     241  822.77   250.7  829.74
   260.3  835.85     270  841.09   327.8     870
#Mann= 3 , 0 , 0
       0     .06       0   184.9    .045       0   202.5     .06       0
Bank Sta=184.9,202.5
XS Rating Curve= 0 ,0
Exp/Cntr=0.3,0.1

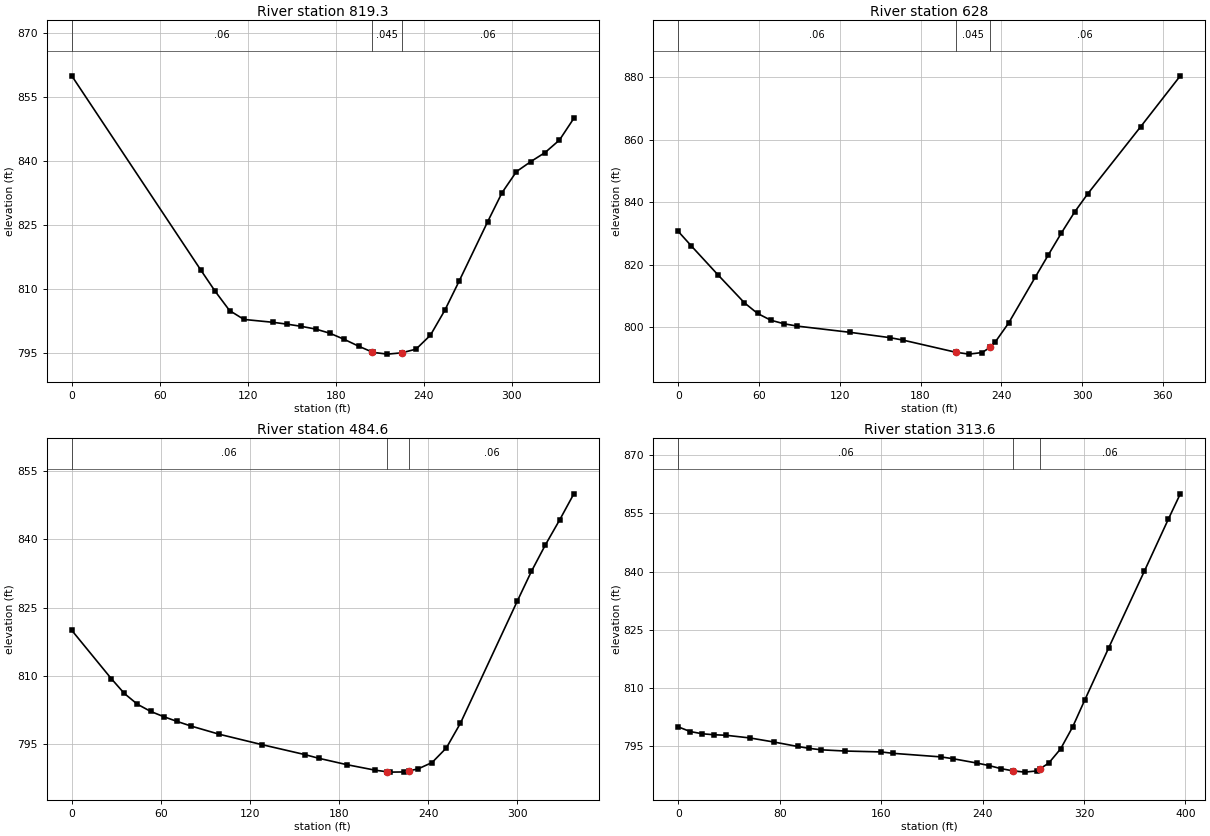
Type RM Length L Ch R = 1 ,819.3   ,198.1,191.2,184.4
XS GIS Cut Line= 2
     1647312.279      324664.493     1647619.888      324514.362
#Sta/Elev= 27
       0     860      88   814.4    97.8  809.41   107.6   804.9   117.4  802.82
   136.9  802.16   146.7  801.72   156.5   801.2   166.3  800.56     176  799.58
   185.8  798.14   195.6  796.54   204.7  795.19   205.4  795.09   215.2  794.68
   224.9  794.98   234.7  795.85   244.5  799.11   254.3  804.95     264  811.75
   283.6   825.8   293.4   832.6   303.2  837.53     313  839.88   322.7     842
   332.5  844.93   342.3  850.03
#Mann= 3 , 0 , 0
       0     .06       0   204.7    .045       0   224.9     .06       0
Bank Sta=204.7,224.9
XS Rating Curve= 0 ,0
Exp/Cntr=0.3,0.1

Type RM Length L Ch R = 1 ,628     ,145.7,143.5,141.3
XS GIS Cut Line= 2
     1647471.045      324861.977     1647742.312      324605.901
#Sta/Elev= 24
       0  830.64     9.8  825.96    29.4  816.81    49.1  807.84    58.9  804.42
    68.7  802.26    78.5  801.12    88.4  800.37   127.6  798.38   157.1  796.69
   166.9   795.9   206.2  792.01     216  791.41   225.8  791.92  231.55  793.55
   235.6  795.34   245.4  801.31   265.1  815.92   274.9  823.09   284.7  830.17
   294.5  836.85   304.3   842.7   343.6  864.13     373  880.37
#Mann= 3 , 0 , 0
       0     .06       0   206.2    .045       0  231.55     .06       0
Bank Sta=206.2,231.55
XS Rating Curve= 0 ,0
Exp/Cntr=0.3,0.1

Type RM Length L Ch R = 1 ,484.6   ,169.6,170.9,172.3
XS GIS Cut Line= 3
      1647575.24      324972.861     1647629.765      324927.709
     1647804.944      324725.621
#Sta/Elev= 27
       0     820    26.6  809.39    35.4  806.13    44.2  803.76    53.1  802.19
    61.9  801.03    70.8     800    80.3  798.97    99.4  797.16   128.1  794.88
   156.8  792.71   166.3  791.89   185.4  790.47   204.5  789.26   212.1  788.93
   214.1  788.84   223.6  788.88   227.1  789.12   233.2  789.54   242.7  790.95
   252.3  794.15   261.8  799.59     300  826.35   309.6  832.95   319.1  838.82
   328.7   844.3   338.2     850
#Mann= 3 , 0 , 0
       0     .06       0   212.1    .045       0   227.1     .06       0
Bank Sta=212.1,227.1
XS Rating Curve= 0 ,0
Exp/Cntr=0.3,0.1

Type RM Length L Ch R = 1 ,313.6   ,314.2,313.6,313
XS GIS Cut Line= 4
     1647655.429      325059.523     1647795.263      324981.769
     1647900.355      324873.257     1647949.857      324804.256
#Sta/Elev= 30
       0  800.01     9.4  798.81    18.8  798.24    28.2  797.98    37.6  797.85
    56.5  797.16    75.3  796.12    94.1  794.97   103.5  794.47   112.9   794.1
   131.8  793.79     160  793.56   169.4   793.2   207.2  792.28   216.6  791.82
   235.5   790.7     245  790.06   254.4  789.27   263.8   788.7   273.3  788.36
   282.7  788.66   285.4  789.23   292.2  790.68   301.6  794.35   311.1     800
   320.5  806.82   339.4  820.27   367.7  840.13   386.5  853.44     396     860
#Mann= 3 , 0 , 0
       0     .06       0   263.8    .045       0   285.4     .06       0
Bank Sta=263.8,285.4
XS Rating Curve= 0 ,0
Exp/Cntr=0.3,0.1

Chan Stop Cuts=-1
Use User Specified Reach Order=0
Composite Channel Slope=5